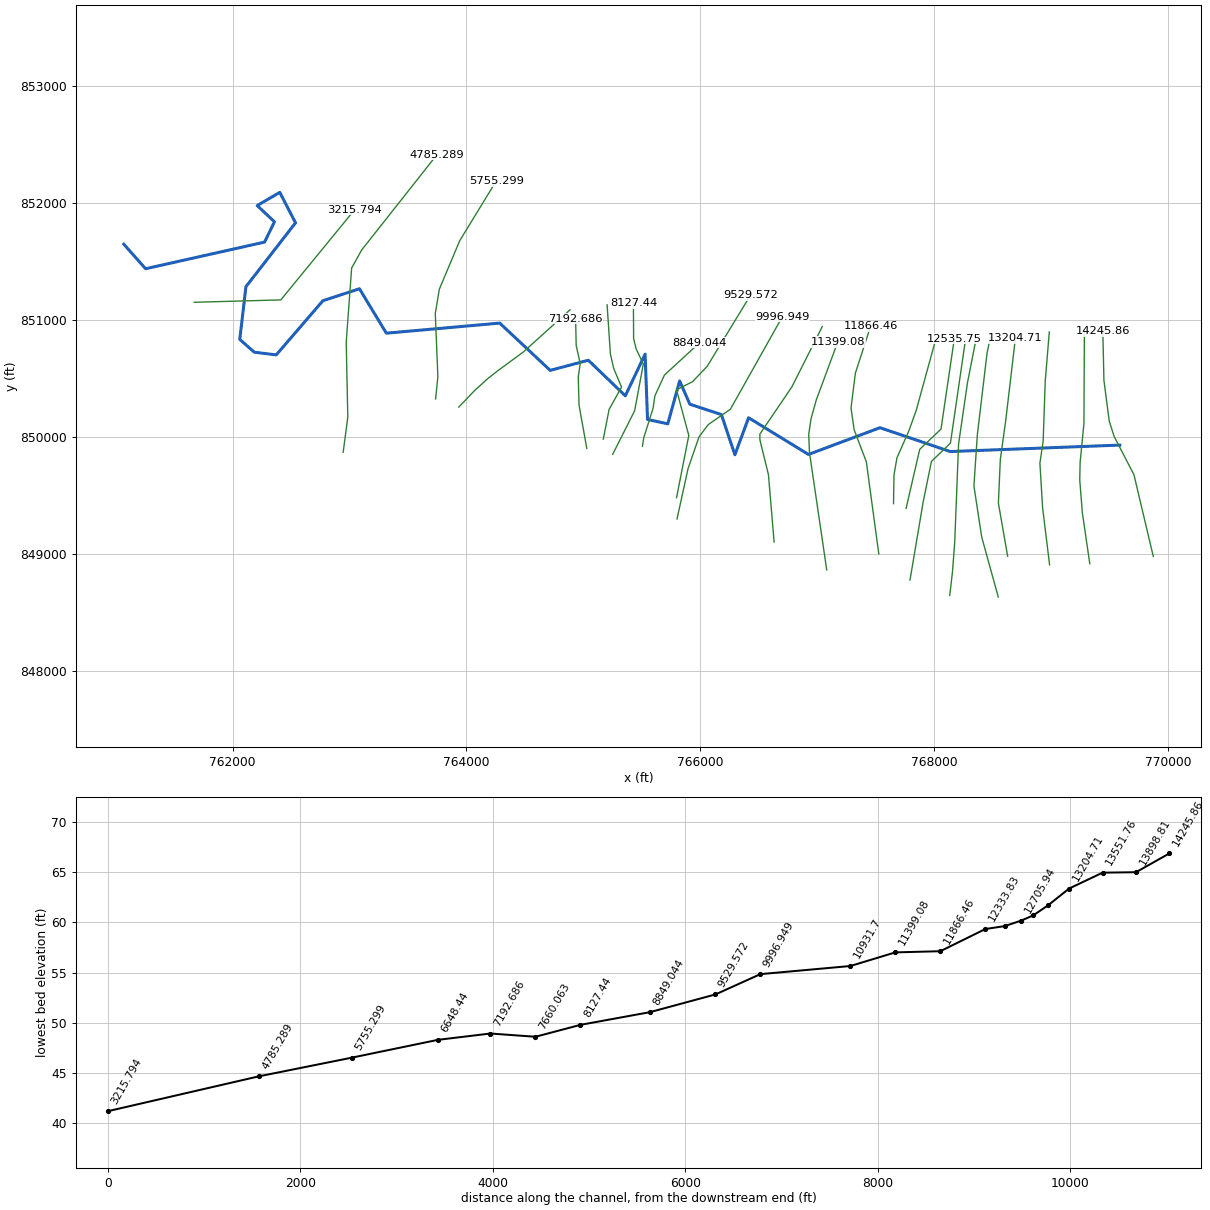
--- 15667_ras.prj (project) ---

Proj Title=15667
Current Plan=p01
Default Exp/Contr=0.3,0.1
English Units
Geom File=g01
Flow File=f01
Plan File=p01
Y Axis Title=Elevation
X Axis Title(PF)=Main Channel Distance
X Axis Title(XS)=Station
BEGIN DESCRIPTION:
RFD model 15667 exported to HEC-RAS
END DESCRIPTION:

--- 15667_ras.p01 (plan) ---

Plan Title=Plan 01
Program Version=4.10
Short Identifier=Plan 01
Geom File=g01
Flow File=f01
Subcritical Flow
Calc Critical at every XS
Secant Critical Depth

--- 15667_ras.f01 (steady flow) ---

Flow Title=Flow 01
Program Version=5.01
Number of Profiles= 6
Profile Names=10yr,25yr,50yr,100yr,100plus,500yr
River Rch & RM=15667,22,14245.86
 2846.97 4721.46 6541.01 8247.7312041.6914453.36
River Rch & RM=15667,22,13898.81
 2850.62 4727.62 6549.63 8258.6912057.6914470.18
River Rch & RM=15667,22,13551.76
  2853.7  4732.8 6556.89 8267.9112071.1614484.33
River Rch & RM=15667,22,13204.71
 3128.39 5194.38 7202.39 9087.5213267.7715729.26
River Rch & RM=15667,22,12986.09
  3130.1 5197.25 7206.41 9092.6213275.2215736.96
River Rch & RM=15667,22,12831.38
 3131.05 5198.85 7208.64 9095.4613279.3715741.24
River Rch & RM=15667,22,12705.94
 3132.19 5200.76 7211.32 9098.8613284.3315746.38
River Rch & RM=15667,22,12535.75
 3132.76 5201.72 7212.66 9100.5613286.8115748.95
River Rch & RM=15667,22,12333.83
 3153.65 5236.92 7261.97 9163.2613378.3615843.83
River Rch & RM=15667,22,11866.46
 3652.65 6067.14 8415.7610619.5915504.6117982.01
River Rch & RM=15667,22,11399.08
 3663.45 6085.34 8441.2410651.98 15551.918029.92
River Rch & RM=15667,22, 10931.7
  3667.7 6092.47 8451.2110664.6415570.3818048.58
River Rch & RM=15667,22,9996.949
 3679.11 6111.65 8478.0510698.7215620.1418098.85
River Rch & RM=15667,22,9529.572
 3769.33 6262.52 8688.4410965.07   1600918487.78
River Rch & RM=15667,22,8849.044
 3807.44 6326.31 8777.4511077.81 16173.618652.23
River Rch & RM=15667,22, 8127.44
 3800.26 6314.28 8760.6311056.4716142.4418620.99
River Rch & RM=15667,22,7660.063
 3814.66 6338.41 8794.3411099.2116204.8518683.45
River Rch & RM=15667,22,7192.686
 3818.91 6345.54 8804.2911111.8216223.2618701.85
River Rch & RM=15667,22, 6648.44
 3821.88 6350.51 8811.22 11120.616236.0818714.65
Boundary for River Rch & Prof#=15667,22,1
Up Type= 0
Dn Type= 2
Boundary for River Rch & Prof#=15667,22,2
Up Type= 0
Dn Type= 2
Boundary for River Rch & Prof#=15667,22,2
Up Type= 0
Dn Type= 2
Boundary for River Rch & Prof#=15667,22,2
Up Type= 0
Dn Type= 2
Boundary for River Rch & Prof#=15667,22,2
Up Type= 0
Dn Type= 2
Boundary for River Rch & Prof#=15667,22,2
Up Type= 0
Dn Type= 2

--- 15667_ras.g01 (geometry) ---

Geom Title=15667
Program Version=4.10

River Reach=15667,22
Reach XY= 30
769588.473465072849930.546629613 768138.03363201849875.293320045
767536.905159831850079.286375612766924.925993115849850.466931164
766413.207243145850164.269014508766296.019743115849847.862764552
766180.134326458850191.612764522765910.603076518850280.154431179
765823.363493085850479.373181194765721.800993204850112.185681164
765548.623909771850149.946097851765527.790576488850708.539847851
765358.519743174850351.769014552765042.113493174850656.456514522
 764716.00755319850569.716310129764284.104204625850974.014744103
763314.486149102850887.787892252763084.451426834851267.562197834
762771.951426834851165.565670058762372.749753624850702.121611997
762184.606067836850725.136844814762060.880102605850834.662476167
762113.543650836851285.800403744762537.576426864851831.798308969
762403.027815729852092.214975595762209.885454625851979.367753327
762357.454899132851840.478864446762272.819482416851666.867753431
761255.024343461851439.003170028761068.346780151 851649.57963258

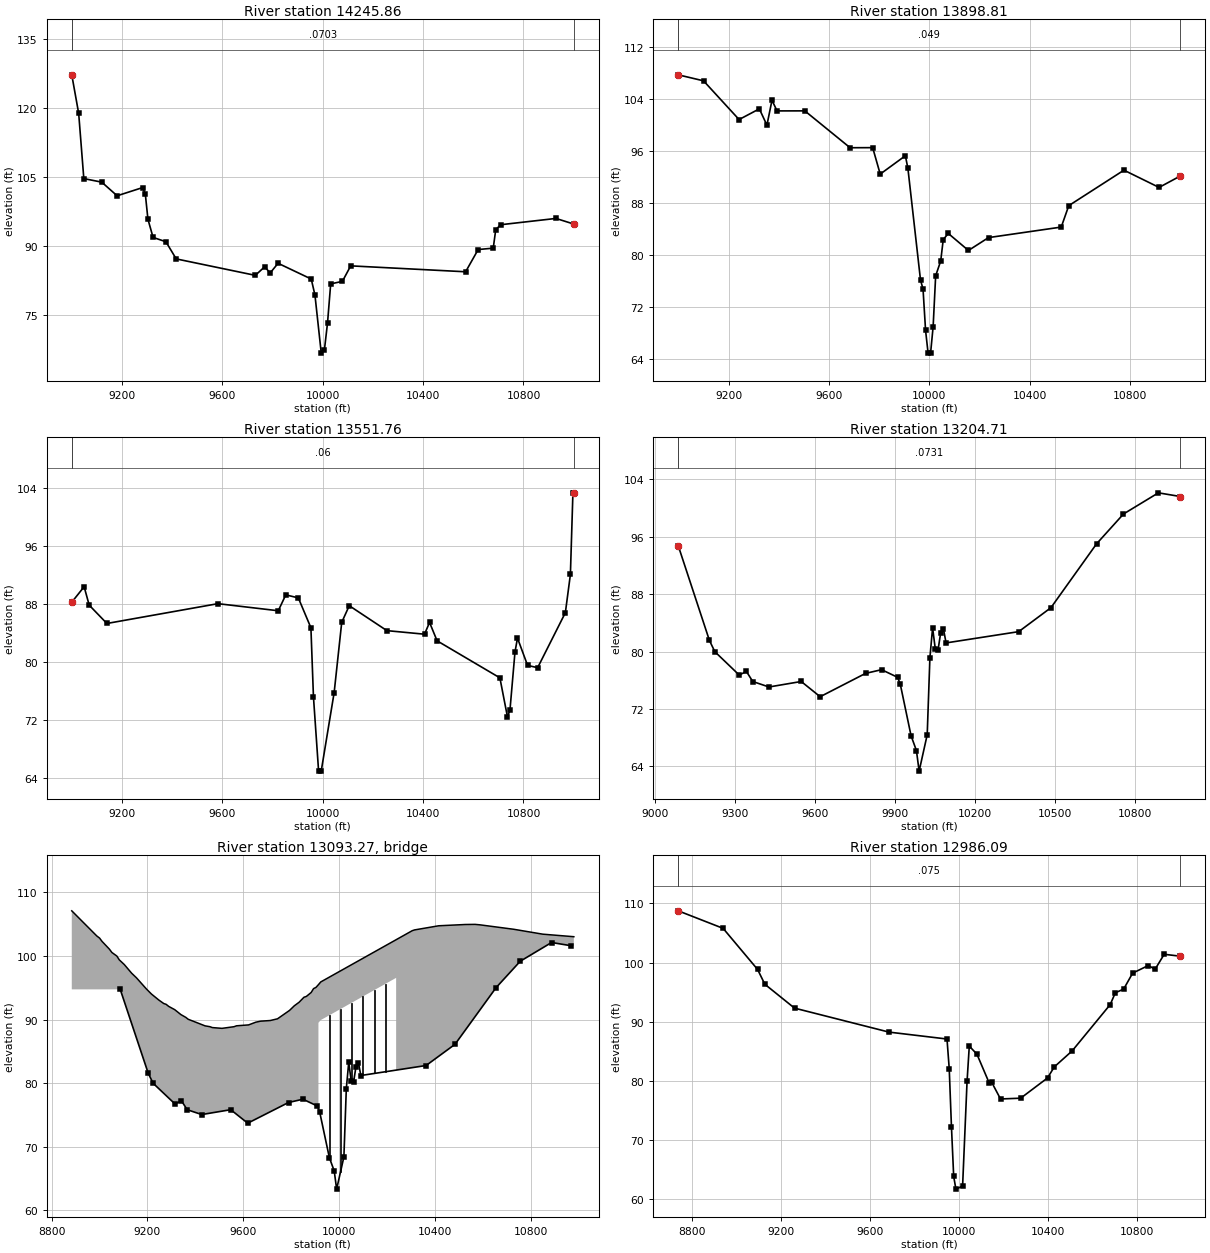
Type RM Length L Ch R = 1 ,14245.86,347.049500,347.049500,347.049500
XS GIS Cut Line= 6
  769874.7038319848977.994028316769709.412784154849676.957676372
769540.231693386850003.532370448769497.900498632850135.059288803
769452.434751561850485.546277339769443.042409128850906.261849827
#Sta/Elev= 30
8999.099127.19139026.686118.81589047.117104.68949118.623103.91489179.915 100.959
9282.227102.74929292.474101.2679 9302.7295.885349323.21391.931169374.44590.99017
9415.43887.270699730.83783.701789768.57285.578839789.78884.195849821.63886.31939
9953.85882.903239968.61779.448179993.79266.8336210006.4167.54522 10018.973.43494
10031.3981.8500610078.0482.39694 10111.285.7609310569.3584.4763510619.4389.30239
 10679.589.6000810689.5193.6272310709.5394.68404 10929.696.0445111000.8794.82278
#Mann= 3 , 0 , 0
8999.099  0.0703       08999.099  0.0703       011000.87  0.0703       0
#XS Ineff= 2 , 0
       09876.568        10262.73       0
Bank Sta=8999.099,11000.87
Exp/Cntr=0.3,0.1

Type RM Length L Ch R = 1 ,13898.81,347.049500,347.049500,347.049500
XS GIS Cut Line= 6
769331.577707112848915.270531144769267.964188059849351.625930548
769245.704996362849631.692169592 769248.90233428849784.357356043
769281.485182977850114.636932283769285.383389247850909.605398336
#Sta/Elev= 30
8999.062107.66999099.978106.74849241.644100.80599322.429102.45059352.68799.94463
9372.858 103.766 9393.03102.13359503.737102.13989684.33396.483059774.38596.49542
9804.38692.437029904.67595.252359914.74293.337299965.07776.175689975.14474.79887
 9985.2168.468099995.27764.9658310005.3565.0158510015.4169.0368310025.4876.83315
10045.6279.1047710055.6982.3916810075.8283.3291210156.15 80.7192 10236.282.69256
10526.2384.3081410556.23 87.595510776.2593.0390710916.3190.3917311000.9892.14495
#Mann= 3 , 0 , 0
8999.062   0.049       08999.062   0.049       011000.98   0.049       0
#XS Ineff= 2 , 0
       0                10208.01       0
Bank Sta=8999.062,11000.98
Exp/Cntr=0.3,0.1

Type RM Length L Ch R = 1 ,13551.76,347.049500,347.049500,347.049500
XS GIS Cut Line= 6
768987.658907084848906.150494501768927.790918786849396.177524809
768904.904722123849775.072901419768932.802913922849965.796178096
 768950.54750159 850479.91561255768985.393192942850898.689164728
#Sta/Elev= 30
8999.06688.246599048.34590.38826 9068.5287.841559139.13585.310959581.87588.04564
9822.38287.066789852.38889.264249902.40288.842569952.55284.714679962.66175.19777
9983.06764.991539993.59864.9205510045.2475.7723810075.42 85.464110105.4387.76749
10255.4984.3224810405.5683.8296110425.5885.4561110455.6182.9173410706.0377.80218
 10736.1 72.433510746.1373.3169910766.1781.35368 10776.283.2975810816.3979.52196
10856.5779.2050110967.0786.7998710987.1692.07583 10997.2103.345511000.91103.3529
#Mann= 3 , 0 , 0
8999.066    0.06       08999.066    0.06       011000.91    0.06       0
#XS Ineff= 2 , 0
       0                10127.67       0
Bank Sta=8999.066,11000.91
Exp/Cntr=0.3,0.1

Type RM Length L Ch R = 1 ,13204.71,218.624400,218.624400,218.624400
XS GIS Cut Line= 5
768628.895234326848979.904322137768549.728567669849434.070988823
768566.395234326849809.070988808768612.228567669850138.237655465
768695.561900983850846.570988808
#Sta/Elev= 30
9086.373 94.75869203.20581.564189223.50679.994479314.86376.736149341.99177.23327
9365.61775.834379426.52275.071799547.38875.836969618.38773.714779788.55576.96644
9848.61477.483219908.674 76.41819918.68375.459469959.03468.285079979.22766.20531
9989.32463.3447510019.6168.4183310029.7179.1569410039.8183.30363 10049.980.37783
   1006080.17392 10070.182.6285710080.19   83.2210090.29 81.2127 10362.682.78344
10483.4386.12464 10654.695.0312910755.2999.1786810886.19102.129110968.32101.6152
#Mann= 3 , 0 , 0
9086.373  0.0731       09086.373  0.0731       010968.32  0.0731       0
#XS Ineff= 2 , 0
       09879.527        10329.25       0
Bank Sta=9086.373,10968.32
Exp/Cntr=0.3,0.1

Type RM Length L Ch R = 3 ,13093.27,,,
BEGIN DESCRIPTION:
END DESCRIPTION:
Bridge Culvert--1,0,-1,-1, 0
Deck Dist Width WeirC Skew NumUp NumDn MinLoCord MaxHiCord MaxSubmerge Is_Ogee
55.092200,108.440000,2.6,0, 54, 52, , , 0.95, 0, 0,0,,
 8884.21 8989.13 9000.07 9010.38 9041.30 9051.61 9072.23 9082.53 9103.15 9134.07
 9154.06 9195.92 9216.53 9247.46 9268.07 9277.75 9288.69 9313.70 9339.65 9359.81
 9369.89 9440.46 9460.62 9470.70 9511.03 9561.44 9571.52 9621.93 9652.17 9672.33
 9712.48 9742.58 9792.74 9812.81 9832.87 9852.94 9862.97 9883.04 9893.07 9903.10
 9913.38 9913.38 9923.1710237.6210237.6210304.2910314.4610415.2310526.2910566.68
10586.8710728.2210849.3710979.03
  107.11  103.14  102.83  102.31  101.08  100.56  100.00   99.40   98.67   97.30
   96.58   94.81   94.03   93.08   92.53   92.41   92.08   91.57   90.79   90.36
   90.06   89.02   88.89   88.75   88.63   88.89   89.03   89.17   89.60   89.76
   89.86   90.13   91.45   92.18   92.74   93.52   93.65   94.27   94.88   95.07
   95.50   95.50   95.93  102.57  102.57  103.98  104.11  104.76  104.96  104.98
  104.91  104.21  103.44  103.04
 -892.89 -896.86 -897.17 -897.69 -898.92 -899.44 -900.00 -900.60 -901.33 -902.70
 -903.42 -905.19 -905.97 -906.92 -907.47 -907.59 -907.92 -908.43 -909.21 -909.64
 -909.94 -910.98 -911.11 -911.25 -911.37 -911.11 -910.97 -910.83 -910.40 -910.24
 -910.14 -909.87 -908.55 -907.82 -907.26 -906.48 -906.35 -905.73 -905.12 -904.93
 -904.50   89.50   89.93   96.57 -897.43 -896.02 -895.89 -895.24 -895.04 -895.02
 -895.09 -895.79 -896.56 -896.96
 8884.21 8989.13 9000.07 9010.38 9041.30 9051.61 9072.23 9082.53 9103.15 9134.07
 9154.06 9195.92 9216.53 9247.46 9268.07 9277.75 9288.69 9313.70 9339.65 9359.81
 9369.89 9440.46 9460.62 9470.70 9511.03 9561.44 9571.52 9621.93 9652.17 9672.33
 9712.48 9742.58 9792.74 9812.81 9832.87 9852.94 9862.97 9883.04 9893.07 9903.10
 9924.44 9924.4410248.6810248.6810304.2910334.5210415.2310465.7110564.3910708.02
10849.3710979.03
  107.11  103.14  102.83  102.31  101.08  100.56  100.00   99.40   98.67   97.30
   96.58   94.81   94.03   93.08   92.53   92.41   92.08   91.57   90.79   90.36
   90.06   89.02   88.89   88.75   88.63   88.89   89.03   89.17   89.60   89.76
   89.86   90.13   91.45   92.18   92.74   93.52   93.65   94.27   94.88   95.07
   95.94   95.94  102.80  102.80  103.98  104.25  104.76  104.90  104.98  104.32
  103.44  103.04
 -892.89 -896.86 -897.17 -897.69 -898.92 -899.44 -900.00 -900.60 -901.33 -902.70
 -903.42 -905.19 -905.97 -906.92 -907.47 -907.59 -907.92 -908.43 -909.21 -909.64
 -909.94 -910.98 -911.11 -911.25 -911.37 -911.11 -910.97 -910.83 -910.40 -910.24
 -910.14 -909.87 -908.55 -907.82 -907.26 -906.48 -906.35 -905.73 -905.12 -904.93
 -904.06   89.94   96.80 -897.20 -896.02 -895.75 -895.24 -895.10 -895.02 -895.68
 -896.56 -896.96
Pier Skew, UpSta & Num, DnSta & Num=  ,9958.27, 2 ,9969.33, 2 , 0 , 0 , 0 ,,
    4.00    4.00
 -903.35   96.65
    4.00    4.00
 -903.12   96.88
Pier Skew, UpSta & Num, DnSta & Num=  ,10005.16, 2 ,10016.22, 2 , 0 , 0 , 0 ,,
    4.00    4.00
 -902.36   97.64
    4.00    4.00
 -902.12   97.88
Pier Skew, UpSta & Num, DnSta & Num=  ,10052.05, 2 ,10063.12, 2 , 0 , 0 , 0 ,,
    4.00    4.00
 -901.36   98.64
    4.00    4.00
 -901.13   98.87
Pier Skew, UpSta & Num, DnSta & Num=  ,10098.94, 2 ,10110.01, 2 , 0 , 0 , 0 ,,
    4.00    4.00
 -900.37   99.63
    4.00    4.00
 -900.14   99.86
Pier Skew, UpSta & Num, DnSta & Num=  ,10145.84, 2 ,10156.90, 2 , 0 , 0 , 0 ,,
    4.00    4.00
 -899.38  100.62
    4.00    4.00
 -899.14  100.86
Pier Skew, UpSta & Num, DnSta & Num=  ,10192.73, 2 ,10203.79, 2 , 0 , 0 , 0 ,,
    4.00    4.00
 -898.38  101.62
    4.00    4.00
 -898.15  101.85
BR Coef=-1 , 0 , 0 ,, 0 ,,,0.8,0,1,0,
WSPro=,,,, 1 ,,,, 0 ,,,, 0 ,,,,-1 ,-1 ,-1 , 0 , 0 , 0 , 0 , 0
BC Design=,, 0 ,, 0 ,,,,,,

Type RM Length L Ch R = 1 ,12986.09,154.711900,154.711900,154.711900
XS GIS Cut Line= 6
768548.782303423848630.926908329768407.115636766849143.426908314
768340.448970079849580.926908329768369.615636766850018.426908329
768452.948970079850718.426908329768482.115636766850855.926908329
#Sta/Elev= 30
8737.235108.74628939.097105.78179094.21298.829189126.76396.329689260.21292.29139
9685.27988.234879946.09887.06534 9956.1282.043699966.14272.210799976.16463.82335
9986.18761.6805410016.2562.19573 10036.379.9014610046.3285.8630110080.5984.51228
10136.5279.5779710146.5479.7862510186.8176.9268810277.4477.0593110398.2980.48375
 10428.5 82.347210509.0785.0612410680.2792.8951810703.0894.8856310740.69 95.5085
10780.9798.2073210851.4799.4982210882.0898.8664410922.97101.395910995.48101.0729
#Mann= 3 , 0 , 0
8737.235   0.075       08737.235   0.075       010995.48   0.075       0
#XS Ineff= 2 , 0
       09882.781        10346.66       0
Bank Sta=8737.235,10995.48
Exp/Cntr=0.3,0.1

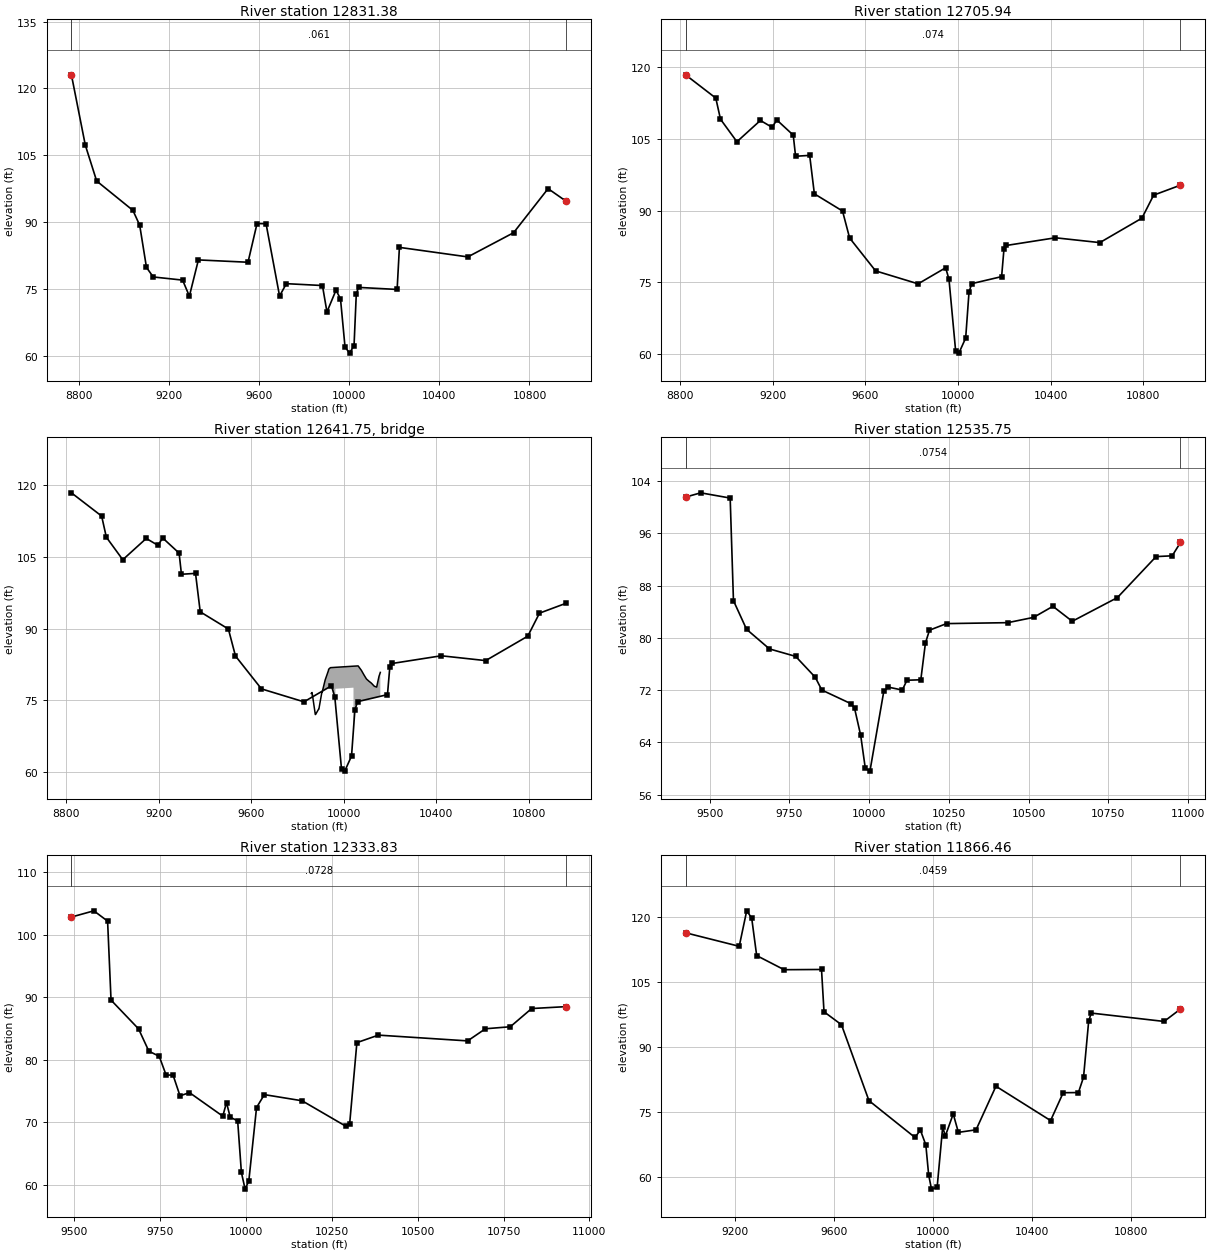
Type RM Length L Ch R = 1 ,12831.38,125.439000,125.439000,125.439000
XS GIS Cut Line= 6
768133.437200248848643.841411173768157.648782402848851.979108721
768176.383424342849105.169913635768209.214898646849939.610066935
768285.462030023850464.458181769768356.092183113850824.400823146
#Sta/Elev= 30
8767.677123.05988829.318107.30218879.70599.256889040.49292.674499070.60789.34631
9100.67279.886699130.73777.74525 9260.9877.042389291.00573.441429331.03981.56732
9551.16881.045059591.18589.715539631.20189.680669691.22673.472699721.23976.24302
9881.38375.824929901.40769.902479941.45374.771259961.47672.85009  9981.5 62.0718
10001.5260.6718510021.5662.3457710031.5873.95027 10041.675.4068610212.7274.94729
10222.8384.3786910526.2982.2419110729.4287.6641110882.4497.5432310963.5194.69114
#Mann= 3 , 0 , 0
8767.677   0.061       08767.677   0.061       010963.51   0.061       0
#XS Ineff= 2 , 0
       0                               0
Bank Sta=8767.677,10963.51
Exp/Cntr=0.3,0.1

Type RM Length L Ch R = 1 ,12705.94,170.182800,170.182800,170.182800
XS GIS Cut Line= 5
767793.631840467848776.158389792767906.131840467849442.825056478
767976.965173781849790.741723135768139.465173781849946.991723135
768266.548507124850819.908389807
#Sta/Elev= 30
8822.965118.45198953.628113.57798973.911109.15779044.901104.43699146.315108.8965
9197.022 107.4549217.304108.99829288.294 105.8259298.435101.39499359.284 101.579
9379.56693.526439501.277 89.92199531.89284.272949644.149 77.38449827.84274.67181
9946.82278.036179961.24975.630359990.10560.5787110003.9960.1570610033.3963.31428
10047.8272.9359210059.4874.7095210188.6976.18294 10198.881.92807 10208.982.70722
10421.1284.3188810613.1283.3077810795.0288.4294910845.5493.2465810961.6695.34188
#Mann= 3 , 0 , 0
8822.965   0.074       08822.965   0.074       010961.66   0.074       0
#XS Ineff= 2 , 0
       0                               0
Bank Sta=8822.965,10961.66
Exp/Cntr=0.3,0.1

Type RM Length L Ch R = 3 ,12641.75,,,
BEGIN DESCRIPTION:
END DESCRIPTION:
Bridge Culvert--1,0,-1,-1, 0
Deck Dist Width WeirC Skew NumUp NumDn MinLoCord MaxHiCord MaxSubmerge Is_Ogee
66.554700,37.073400,2.6,0, 34, 34, , , 0.95, 0, 0,0,,
 9859.38 9860.83 9862.73 9863.94 9876.87 9878.09 9891.01 9892.23 9905.15 9906.37
 9919.30 9920.51 9933.44 9934.66 9942.00 9963.73 9963.7310041.8210041.8210061.95
10074.8610075.9110076.1510086.5710096.3010098.0910109.6110116.4610121.1310126.30
10131.8610141.9510152.0510157.82
   76.44   76.48   76.62   76.28   72.01   72.03   73.13   73.14   76.67   76.67
   79.22   79.40   81.20   81.50   81.83   81.90   81.90   82.14   82.14   82.20
   81.34   81.27   81.25   80.36   79.58   79.45   78.95   78.70   78.49   78.22
   77.94   77.76   80.01   80.84
 -923.56 -923.52 -923.38 -923.72 -927.99 -927.97 -926.87 -926.86 -923.33 -923.33
 -920.78 -920.60 -918.80 -918.50 -918.17 -918.10   77.40   77.64 -917.86 -917.80
 -918.66 -918.73 -918.75 -919.64 -920.42 -920.55 -921.05 -921.30 -921.51 -921.78
 -922.06 -922.24 -919.99 -919.16
 9859.38 9860.83 9862.73 9863.94 9876.87 9878.09 9891.01 9892.23 9905.15 9906.37
 9919.30 9920.51 9933.44 9934.66 9942.00 9959.25 9959.2510037.3410037.3410061.95
10074.8610075.9110076.1510086.5710096.3010098.0910109.6110116.4610121.1310126.30
10131.8610141.9510152.0510157.82
   76.44   76.48   76.62   76.28   72.01   72.03   73.13   73.14   76.67   76.67
   79.22   79.40   81.20   81.50   81.83   81.88   81.88   82.12   82.12   82.20
   81.34   81.27   81.25   80.36   79.58   79.45   78.95   78.70   78.49   78.22
   77.94   77.76   80.01   80.84
 -923.56 -923.52 -923.38 -923.72 -927.99 -927.97 -926.87 -926.86 -923.33 -923.33
 -920.78 -920.60 -918.80 -918.50 -918.17 -918.12   77.38   77.62 -917.88 -917.80
 -918.66 -918.73 -918.75 -919.64 -920.42 -920.55 -921.05 -921.30 -921.51 -921.78
 -922.06 -922.24 -919.99 -919.16
BR Coef=-1 , 0 , 0 ,, 0 ,,,0.8,0,1,0,
WSPro=,,,, 1 ,,,, 0 ,,,, 0 ,,,,-1 ,-1 ,-1 , 0 , 0 , 0 , 0 , 0
BC Design=,, 0 ,, 0 ,,,,,,

Type RM Length L Ch R = 1 ,12535.75,201.919400,201.919400,201.919400
XS GIS Cut Line= 4
767760.298507124849388.658389807767876.617951542849893.866723135
768058.909618258850067.477834255768172.798507124850840.741723135
#Sta/Elev= 30
9424.186101.5287 9471.74102.17979564.095101.37879574.35685.687859615.40381.30873
9687.23478.304019769.32777.162399830.89773.96384 9851.4272.012639944.255 69.8917
9954.18769.195359973.25565.085269987.75560.0339610002.2659.6114710045.7671.83259
10060.2672.4565410103.7672.0122410118.26 73.511610161.7673.5848210176.2679.20369
10188.9581.1696110242.3882.1761210434.4382.32029 10515.383.1284710575.94 84.8227
10636.5982.53189 10778.186.15323 10899.4 92.425410949.9392.5474810975.9594.58495
#Mann= 3 , 0 , 0
9424.186  0.0754       09424.186  0.0754       010975.95  0.0754       0
#XS Ineff= 2 , 0
       0                               0
Bank Sta=9424.186,10975.95
Exp/Cntr=0.3,0.1

Type RM Length L Ch R = 1 ,12333.83,467.377200,467.377200,467.377200
XS GIS Cut Line= 6
767652.888180971849429.738835275767656.609930277 849673.84536016
767682.301559269849822.213257834767782.784726679850049.787232071
767846.293951809850225.385902718768007.710045069850812.582356125
#Sta/Elev= 30
9492.876102.79119558.139103.78519598.141102.14169608.14189.52349 9688.1784.92835
9718.22281.358219748.31380.547679768.41777.542099788.56777.546779808.82974.22523
9836.38574.740529933.25670.976229944.08873.145479954.91970.811759976.58370.22672
9987.41561.981379998.24659.3203410009.0660.6423510031.5172.3570610054.1974.42052
10164.0973.4362910291.7269.3563910302.2869.6839610323.4282.7262710385.99 83.9258
10645.6483.0041510697.3784.94189 10769.885.2632110831.8888.1733310932.8588.47973
#Mann= 3 , 0 , 0
9492.876  0.0728       09492.876  0.0728       010932.85  0.0728       0
#XS Ineff= 2 , 0
       0                               0
Bank Sta=9492.876,10932.85
Exp/Cntr=0.3,0.1

Type RM Length L Ch R = 1 ,11866.46,467.377200,467.377200,467.377200
XS GIS Cut Line= 6
767526.739902109848999.808209161 767420.10937523849788.056058303
767316.174762874850060.760447907767289.103822552850246.846096114
767326.562645991850546.140162992767456.670543013850947.418032485
#Sta/Elev= 30
 8999.09116.35899216.129113.22919246.386121.43129266.558119.7687 9286.73111.0888
9397.674107.82329548.961107.87759559.04798.101139629.648 95.10979740.83377.56267
9926.97569.060229948.77870.759479970.83667.347799982.29160.401099993.74657.11573
 10016.657.5419810039.0171.4778610049.6769.3908210081.6574.4960710102.49 70.2352
10173.9870.8207110254.4380.8937510475.4572.9577610526.4479.3975810587.9679.43108
10608.68 82.9805 10629.495.8940210639.7797.8022410934.46 95.867611000.8398.73686
#Mann= 3 , 0 , 0
 8999.09  0.0459       0 8999.09  0.0459       011000.83  0.0459       0
#XS Ineff= 2 , 0
       0                10165.06       0
Bank Sta=8999.09,11000.83
Exp/Cntr=0.3,0.1

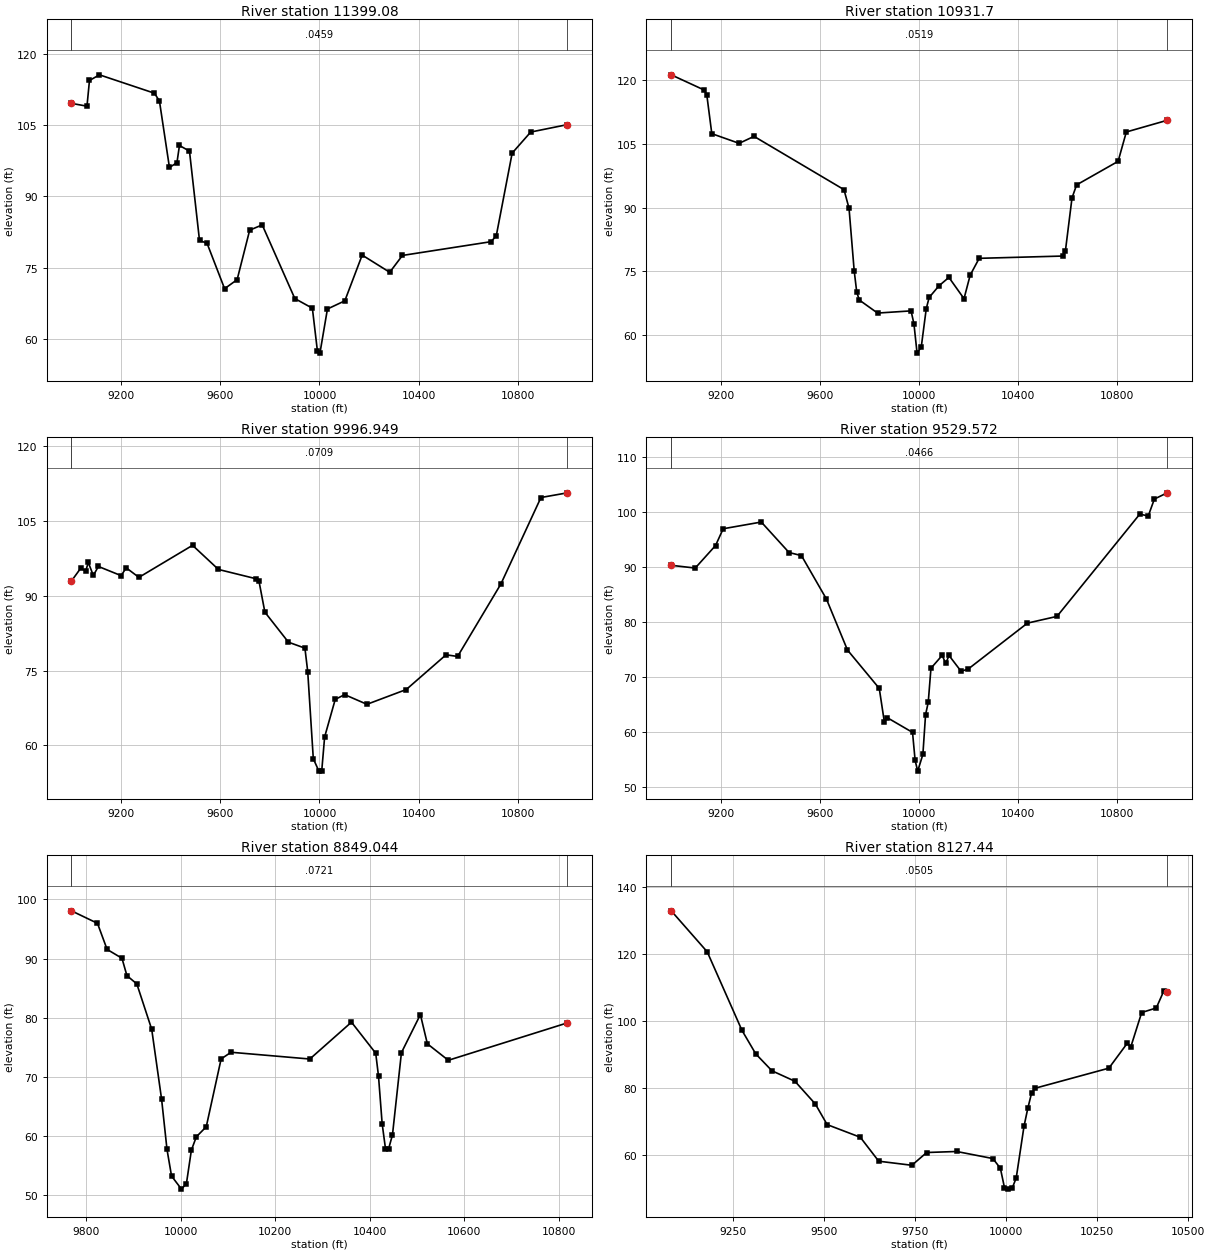
Type RM Length L Ch R = 1 ,11399.08,467.377100,467.377100,467.377100
XS GIS Cut Line= 6
767081.454824259848862.856404483 766933.88019512849866.824516476
766927.311149902850022.890095144766947.591689966850157.368294209
766992.243240829 850317.31950135 767175.98429231850812.657074209
#Sta/Elev= 30
8999.016109.51429061.625108.9259  9071.7 114.3289111.999115.51669333.878111.6517
9354.073110.01429394.46396.037859424.75697.043429434.853100.6609 9475.3499.47063
9515.83180.68672  9546.280.10281 9617.0670.547699667.67472.444969718.28882.84929
9768.90383.96537  9900.568.47646 9971.36 66.44249991.675 57.451310001.8856.99885
10032.1466.2776610102.3467.9970410172.3777.6136310283.5773.9998810334.8777.53932
10692.2280.4305910713.5281.6443410777.7399.0597910852.64103.4842 11000.9105.0497
#Mann= 3 , 0 , 0
8999.016  0.0459       08999.016  0.0459       0 11000.9  0.0459       0
#XS Ineff= 2 , 0
       09921.493        10236.04       0
Bank Sta=8999.016,11000.9
Exp/Cntr=0.3,0.1

Type RM Length L Ch R = 1 , 10931.7,934.754400,934.754400,934.754400
XS GIS Cut Line= 6
766631.336249177849101.712398704766582.712963325849678.398438228
 766509.91059679 849974.45577067 766509.25653392850024.396975093
766783.305634675850428.378774965 767043.02717189 850944.09085131
#Sta/Elev= 30
8999.205121.33129132.847117.72649142.874116.53839162.927107.4446 9273.22105.1613
9333.379106.80759696.39294.235249716.82689.821269737.52575.11531 9747.8970.05434
9758.25468.177519831.89165.10041  9967.165.616429978.71262.581249991.36655.64492
10008.2257.0706310028.5566.1676410040.2468.7906910079.94  71.54510119.8773.51774
10180.83 68.498610205.6774.0435510242.0578.0200710578.9178.5577210590.1879.83096
10616.66 92.268910635.2695.3541610802.73100.912110835.93107.843111000.96110.6003
#Mann= 3 , 0 , 0
8999.205  0.0519       08999.205  0.0519       011000.96  0.0519       0
#XS Ineff= 2 , 0
       0                10147.33       0
Bank Sta=8999.205,11000.96
Exp/Cntr=0.3,0.1

Type RM Length L Ch R = 1 ,9996.949,467.377200,467.377200,467.377200
XS GIS Cut Line= 6
 765800.75705943849298.401077657765895.005198868849728.349220079
765989.083100459850000.922237169  766068.1698883850106.009003381
 766257.42071806850237.318235054 766701.94847133851028.727110091
#Sta/Elev= 30
8999.127 92.93889036.41195.492479056.78594.946559066.97396.656559087.34794.03742
9107.72295.850839199.60794.008619220.05395.578269271.31993.662629487.821100.0836
9592.33195.248399744.36593.384159755.85492.920919779.70886.692919874.69880.67755
9941.30679.480939952.58574.799829975.14357.325359997.70154.8374810009.1354.84577
10020.8561.6815810063.6569.2057410101.6370.1673210191.6368.2257710350.3971.19072
10510.92  78.14810557.5477.8153510732.3892.3520410893.89109.663611000.86110.6028
#Mann= 3 , 0 , 0
8999.127  0.0709       08999.127  0.0709       011000.86  0.0709       0
#XS Ineff= 2 , 0
       0                10180.38       0
Bank Sta=8999.127,11000.86
Exp/Cntr=0.3,0.1

Type RM Length L Ch R = 1 ,9529.572,680.527700,680.527700,680.527700
XS GIS Cut Line= 6
765796.631982074849480.511473003765901.545980468850012.684098566
765796.660233305850403.449425301765933.965650073850472.766279855
766059.780964469 850605.39686793766429.302342243 851212.67154833
#Sta/Elev= 30
8999.369 90.24269096.236 89.7414 9178.2593.840489209.00596.888629362.78198.10931
9474.714 92.56789524.88992.004619625.68684.109149710.56474.835189838.84267.86318
9859.53761.725399869.88462.569949973.10959.861749983.56554.76991 9994.0252.81935
 10014.955.8602410025.6563.0569910036.51 65.334910047.4871.5273310092.5273.84952
10107.2372.4213810120.4173.84393 10168.870.9893210196.6671.3423710436.89 79.7309
10556.0480.9543510890.3699.5557710924.3299.19935   10949102.2884 11000.9103.4199
#Mann= 3 , 0 , 0
8999.369  0.0466       08999.369  0.0466       0 11000.9  0.0466       0
#XS Ineff= 2 , 0
       0                10130.25       0
Bank Sta=8999.369,11000.9
Exp/Cntr=0.3,0.1

Type RM Length L Ch R = 1 ,8849.044,721.603800,721.603800,721.603800
XS GIS Cut Line= 6
765505.090276152849920.638972029765516.158558428849992.582806826
765596.403604895850247.153299093765611.225527018850351.208422035
765693.251074821850529.394497052765993.255711198850805.656015888
#Sta/Elev= 30
9769.27298.075679824.27295.966419844.59691.558499876.05190.063989886.53687.12674
9907.50785.724539938.96278.058599959.93266.20266 9971.2657.775989980.90253.27089
10001.8751.0597510012.3651.9974210022.84 57.644310033.3359.89963 10054.361.59754
10085.7573.0580110106.7274.18207 10273.373.0402410361.3779.2661910412.6274.02301
10418.5270.1597410426.22 62.120110433.2857.9115210439.8157.8513810448.0460.21235
   1046774.1148910507.0980.5500110521.86 75.608510566.1472.8250510818.0779.15048
#Mann= 3 , 0 , 0
9769.272  0.0721       09769.272  0.0721       010818.07  0.0721       0
#XS Ineff= 2 , 0
       0                10382.12       0
Bank Sta=9769.272,10818.07
Exp/Cntr=0.3,0.1

Type RM Length L Ch R = 1 , 8127.44,467.377200,467.377200,467.377200
XS GIS Cut Line= 6
765250.519783884849851.462207839765438.680582553 850225.01673454
765512.366683036850623.449522316765451.189500213850753.584942535
765429.564985722850841.638869151 765427.85065891851144.977850468
#Sta/Elev= 30
9079.673132.80719178.549120.58149273.98297.152619311.92490.132149356.38385.09415
9419.54381.966669475.52775.192899508.04269.038129599.11265.269879649.70658.12767
9740.77656.910269781.46360.721549863.87661.023839963.36158.919559983.931 56.0107
9995.17450.2444810005.9249.7979710016.6850.1786910027.4453.1177210048.9268.59374
10059.3373.9278510069.7478.4933710080.15 79.915710282.0485.8803510332.0793.24269
10342.0892.1653810372.11102.472910412.21103.828710432.28 108.74710442.29108.4773
#Mann= 3 , 0 , 0
9079.673  0.0505       09079.673  0.0505       010442.29  0.0505       0
#XS Ineff= 2 , 0
       09830.593                       0
Bank Sta=9079.673,10442.29
Exp/Cntr=0.3,0.1

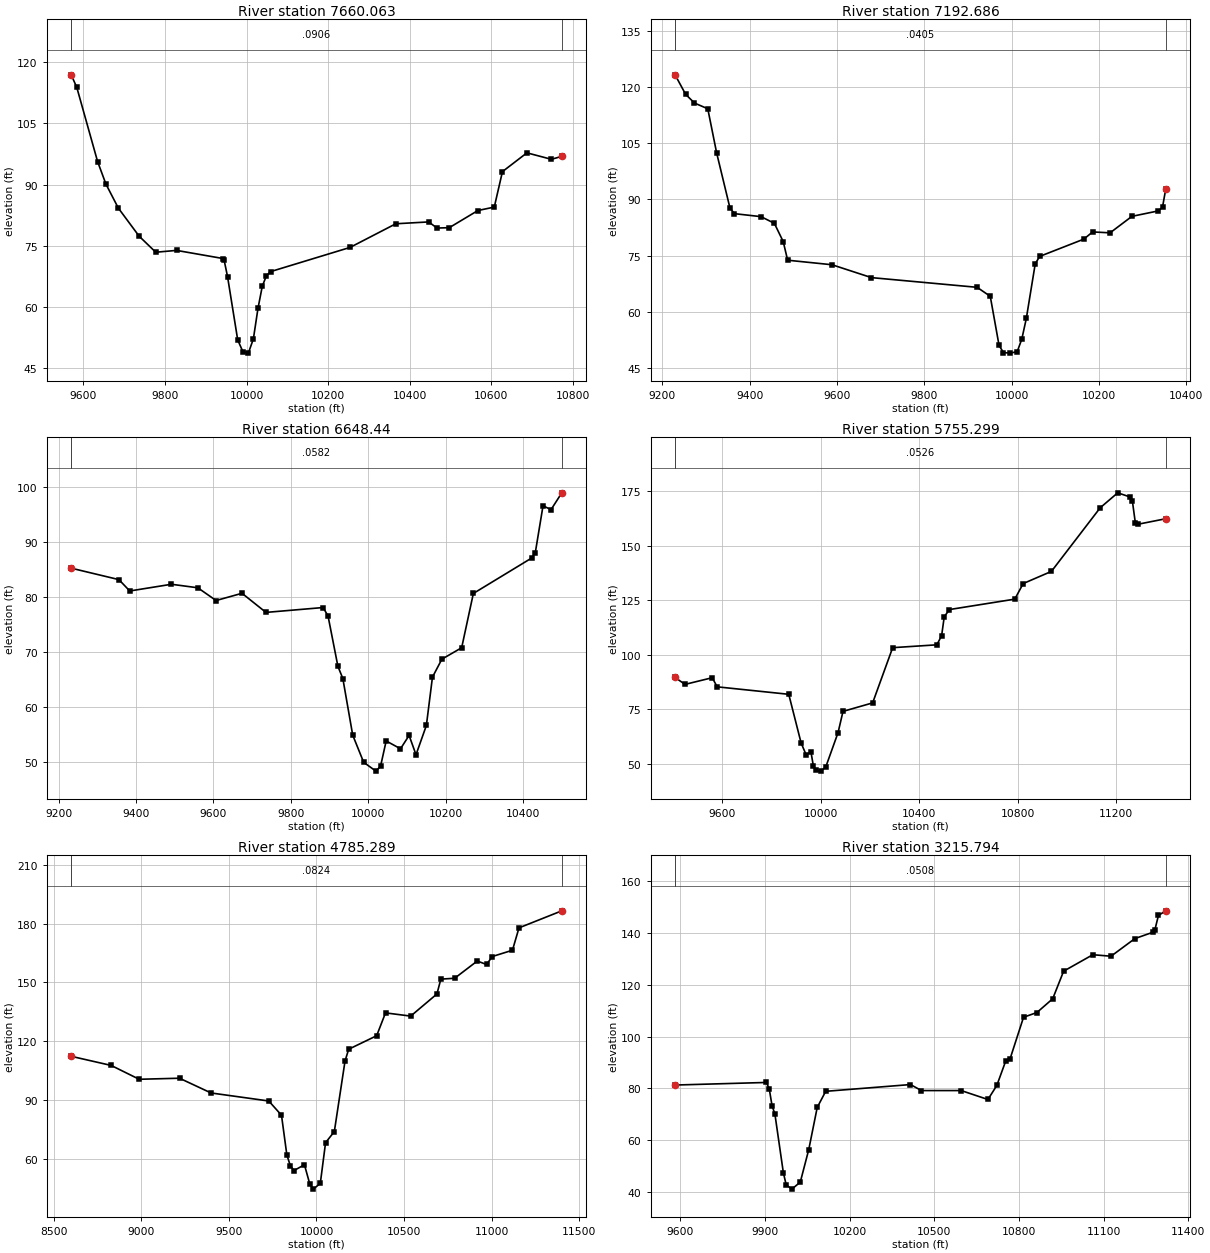
Type RM Length L Ch R = 1 ,7660.063,467.377100,467.377100,467.377100
XS GIS Cut Line= 6
765170.274737418849981.514524549765220.082007647850236.085016817
 765326.46598807850426.535560682765259.073718101850586.175199658
765230.969719052850709.510503218765202.699768397851130.494459849
#Sta/Elev= 30
9569.926116.93279583.667113.83989634.61595.653069654.995 90.12959685.56384.20461
9736.51277.31436 9777.2773.382949828.21873.832979941.80271.844429944.68171.51456
9953.174 67.42329978.12951.86393 9991.1648.8936610004.2148.6152110016.5652.11618
10027.8659.6074310038.3565.0145610048.3867.5860610058.6768.6233510253.5574.56297
10365.7780.3712110446.48 80.824110466.6679.3192410496.8179.4096710567.0583.62431
10607.1684.4665110627.17  93.172 10687.297.7830710747.2196.1929210772.7296.92086
#Mann= 3 , 0 , 0
9569.926  0.0906       09569.926  0.0906       010772.72  0.0906       0
#XS Ineff= 2 , 0
       0                               0
Bank Sta=9569.926,10772.72
Exp/Cntr=0.3,0.1

Type RM Length L Ch R = 1 ,7192.686,544.245800,544.245800,544.245800
XS GIS Cut Line= 6
765029.154138446849901.269478053764962.744444788850272.056934208
 764955.89089188850513.762277514764972.855606645850626.238665283
764938.308231801850782.804690644764933.446115166 851012.30598256
#Sta/Elev= 30
9229.163123.32299253.271 118.1189273.589115.78199304.067114.25069324.385 102.419
9354.86287.704259365.02186.215519425.97685.416159456.453 83.63929476.77278.75741
9486.93173.772779588.52272.560379678.82369.120499920.84966.527159950.94364.12205
9971.07850.980539981.232 49.07939997.14448.9372310012.6849.3519510023.1852.69422
10033.4858.2015110053.9772.8562510064.2274.7959310165.2179.4080710185.2781.33305
 10225.381.0904810275.3285.4966910335.35 86.942510345.35 87.939410352.6692.72452
#Mann= 3 , 0 , 0
9229.163  0.0405       09229.163  0.0405       010352.66  0.0405       0
#XS Ineff= 2 , 0
       0                               0
Bank Sta=9229.163,10352.66
Exp/Cntr=0.3,0.1

Type RM Length L Ch R = 1 , 6648.44,893.141300,893.141300,893.141300
XS GIS Cut Line= 6
 763933.79560897850255.333462204764072.323514616850399.905742559
764180.094156371850497.379339064764265.845082033850564.961678799
 764488.09211699850728.375980705764885.640581302851087.665661672
#Sta/Elev= 30
9232.72885.195649355.81583.119069383.92881.05167 9491.5682.270579559.60281.63235
9606.79279.318659673.699 80.63129735.57577.157679883.09178.042289895.82676.50283
9921.29567.35142 9934.0365.142269959.49954.858159987.75749.9222110019.3648.31171
10031.4149.2038810045.8853.7976210082.8652.3725810105.0754.7958110122.9451.29535
10149.66 56.608510165.3965.3947710189.7368.66045 10240.870.7361910270.9780.60282
10421.1887.02589 10430.887.9756810450.8696.54642 10471.495.8236910499.3498.88929
#Mann= 3 , 0 , 0
9232.728  0.0582       09232.728  0.0582       010499.34  0.0582       0
#XS Ineff= 2 , 0
       0                               0
Bank Sta=9232.728,10499.34
Exp/Cntr=0.3,0.1

Type RM Length L Ch R = 1 ,5755.299,970.009800,970.009800,970.009800
XS GIS Cut Line= 6
763735.935188919850325.254061788763755.245515168850515.133691221
763733.154484928851055.271997049763767.686503291851263.864231795
763942.105185658851678.627858311764253.552346617852188.177829295
#Sta/Elev= 30
 9408.74 89.48749449.063 86.33269559.65789.387299579.68285.204749870.32881.78075
9920.48459.463919940.52454.124049960.56355.27575 9970.5848.703649980.584 46.8417
10000.5946.5448610020.5948.4533210070.5964.22627 10090.673.9500110210.9577.84471
10292.24103.167310471.64104.474310491.06108.664110501.71117.374310523.01120.6559
10788.17125.429510822.26132.5726 10936.9138.153111135.11 167.34811206.09174.1864
 11257.9172.226811265.46170.549711277.43160.576111289.39159.8005 11400.9 162.298
#Mann= 3 , 0 , 0
 9408.74  0.0526       0 9408.74  0.0526       0 11400.9  0.0526       0
#XS Ineff= 2 , 0
       0                               0
Bank Sta=9408.74,11400.9
Exp/Cntr=0.3,0.1

Type RM Length L Ch R = 1 ,4785.289,1569.494500,1569.494500,1569.494500
XS GIS Cut Line= 6
762945.335002126849869.538715798762984.890593265 850170.20899413
762971.187712348 850810.08112511763017.732037849851445.638433293
763103.575099066851599.492186366763747.589886127852414.579905291
#Sta/Elev= 30
 8599.17 112.3488827.235107.70328987.542100.64489217.677101.18199397.87993.66968
9727.546 89.58099800.09282.331869830.61462.151189850.79356.534629871.87854.15524
9931.07257.11175 9961.3247.392769981.485 44.680110021.6947.5900910051.7668.34484
10101.8374.0099110162.93109.944810183.74115.947210343.58 122.83410394.07134.4745
10537.96132.829610687.67144.101810710.15151.667210788.93152.109110917.98160.8873
10971.21159.126411003.82163.1807 11119.1166.392711156.37177.7902 11400.9 186.464
#Mann= 3 , 0 , 0
 8599.17  0.0824       0 8599.17  0.0824       0 11400.9  0.0824       0
#XS Ineff= 2 , 0
       0                               0
Bank Sta=8599.17,11400.9
Exp/Cntr=0.3,0.1

Type RM Length L Ch R = 1 ,3215.794,0.000000,0.000000,0.000000
XS GIS Cut Line= 3
761671.349248111851152.063363165762411.729125351851172.467533022
763044.258390635851944.911105767
#Sta/Elev= 30
9581.103 81.31259904.87782.307689914.88179.840879924.885 73.31069934.88970.17813
  9964.947.532569974.90442.884839994.91141.2151810024.9243.9182310054.9356.45675
10084.9572.6841810114.9678.8962110415.5181.4991610454.2979.1836710595.2579.18635
10689.9675.7431710721.5381.1461110753.0990.5722810768.8891.5328910816.23107.4209
10863.58 109.24510919.59114.541310958.36125.174411061.76131.510811126.38130.9382
11210.83137.721511273.96140.139611281.48140.956511294.41146.644311320.14 148.423
#Mann= 3 , 0 , 0
9581.103  0.0508       09581.103  0.0508       011320.14  0.0508       0
#XS Ineff= 2 , 0
       0                               0
Bank Sta=9581.103,11320.14
Exp/Cntr=0.3,0.1